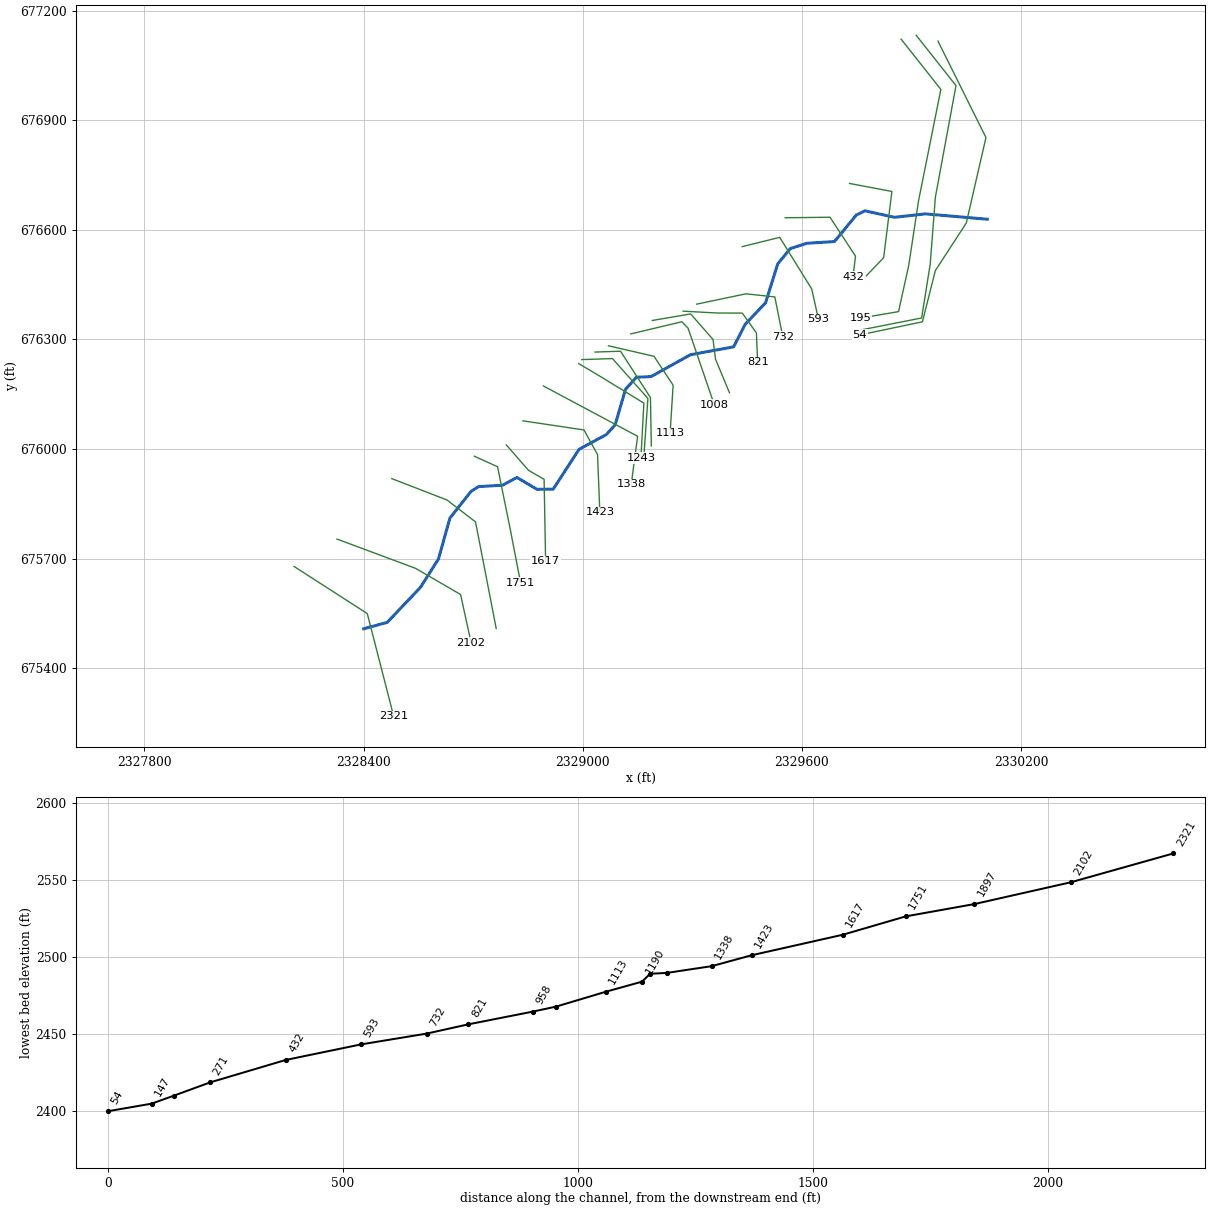
--- REDCK2.prj (project) ---

Proj Title=REDCK2
Current Plan=p01
Default Exp/Contr=0,0
English Units
Geom File=g01
Flow File=f01
Plan File=p01
Background Map Layer=Inundation Boundary (P100yr Value_0)
BEGIN DESCRIPTION:
----------MODEL BY WOOD PLC 2022----------
AFH study
Randolph County, WV
HEC-RAS Version: RAS 6.2
Vertical Datum: NAVD88
Projection: NAD 1983 StatePlane West Virginia S FIPS 4702 (US Feet)
Terrain: 1-meter LIDAR (FEMA Region III 3DEP collected 2016-2018)
Land Use: 2019 NLCD
Hydrologic Method:
WV SIR2010-5033 regression equations
Additional Model Notes:
None
END DESCRIPTION:
DSS Export Rating Curves= 0
DSS Export Rating Curve Sorted= 0
DSS Export Volume Flow Curves= 0
DXF OffsetX= 0
DXF OffsetY= 0
DXF ScaleX= 0
DXF ScaleY= 0

--- REDCK2.p01 (plan) ---

Plan Title=Floodplain
Program Version=6.20
Short Identifier=Floodplain
Geom File=g01
Flow File=f01
Subcritical Flow
K Sum by GR= 0
Std Step Tol= 0.01
Critical Tol= 0.01
Num of Std Step Trials= 20
Max Error Tol= 0.3
Flow Tol Ratio= 0.001
Split Flow NTrial= 30
Split Flow Tol= 0.02
Split Flow Ratio= 0.02
Log Output Level= 0
Friction Slope Method= 1
Unsteady Friction Slope Method= 2
Unsteady Bridges Friction Slope Method= 1
Parabolic Critical Depth
Global Vel Dist= 0 , 0 , 0
Global Log Level= 0
CheckData=False
Encroach Param=-1 ,0,0, 0
Mapping Interval=1HOUR
Computation Time Step Use Courant=        0
Computation Time Step Use Time Series=    0
Computation Time Step Count To Double=0
Computation Time Step Max Doubling=0
Computation Time Step Max Halving=0
Computation Time Step Residence Courant=0
Run HTab= 0
Run UNet= 0
Run Sediment= 0
Run PostProcess= 0
Run WQNet= 0
Run RASMapper=-1
UNET Theta= 0
UNET Theta Warmup= 0
UNET ZTol= 0
UNET ZSATol= 0
UNET MxIter= 0
UNET Max Iter WO Improvement= 0
UNET MaxInSteps= 0
UNET DtIC= 0
UNET DtMin= 0
UNET MaxCRTS= 0
UNET WFStab= 0
UNET SFStab= 0
UNET WFX= 1
UNET SFX= 1
UNET Gravity=32.174
UNET 1D Methodology=Finite Difference
UNET DSS MLevel= 1
UNET Pardiso=0
UNET DZMax Abort= 0
UNET Use Existing IB Tables= 0
UNET Froude Reduction=False
UNET Froude Limit= 0
UNET Froude Power= 0
UNET D1 Cores= 0
UNET WindReference=Eulerian
UNET WindDragFormulation=Hsu (1988)
UNET D2 Coriolis=0
UNET D2 Cores= 0
UNET D2 Theta= 1
UNET D2 Theta Warmup= 1
UNET D2 Z Tol= 0.01
UNET D2 Volume Tol= 0.01
UNET D2 Max Iterations= 20
UNET D2 Equation= 0
UNET D2 RampUpFraction=0.1
UNET D2 TimeSlices= 1
UNET D2 Turbulence Formulation=Non-Conservative (original)
UNET D2 Eddy Viscosity=0.3
UNET D2 Transverse Eddy Viscosity=0.1
UNET D2 Smagorinsky Mixing=0
UNET D2 BCVolumeCheck=0
UNET D2 Cores=0
UNET D2 SolverType=PARDISO (Direct)
UNET D2 Minimum Iterations= 2147483647
UNET D2 Maximum Iterations= 2147483647
UNET D2 Restart Number= 10
UNET D2 Relaxation Coeff=1.3
UNET D2 SOR Precondition Iterations= 10
UNET D2 ILUT Maximum Fill= 8
UNET D2 ILUT Tolerance=1E-08
UNET D1D2 MaxIter= 0
UNET D1D2 ZTol=0.01
UNET D1D2 QTol=0.1
UNET D1D2 MinQTol=1
Write IC File= 0
Write IC File at Fixed DateTime=0
Write IC File at Sim End=0
Echo Input=False
Echo Parameters=False
Echo Output=False
Write Detailed= 0
HDF Write Warmup=0
HDF Write Time Slices=0
HDF Flush=0
HDF Compression= 1
HDF Chunk Size= 1
HDF Spatial Parts= 1
HDF Use Max Rows=0
HDF Fixed Rows= 1
Calibration Method= 0
Calibration Iterations= 20
Calibration Max Change=0.05
Calibration Tolerance=0.2
Calibration Maximum=1.5
Calibration Minimum=0.5
Calibration Optimization Method= 1
WQ AD Non Conservative
WQ ULTIMATE=-1
WQ Max Comp Step=1HOUR
WQ Output Interval=15MIN
WQ Output Selected Increments= 0
WQ Output face flow=0
WQ Output face velocity=0
WQ Output face area=0
WQ Output face dispersion=0
WQ Output cell volume=0
WQ Output cell surface area=0
WQ Output cell continuity=0
WQ Output cumulative cell continuity=0
WQ Output face conc=0
WQ Output face dconc_dx=0
WQ Output face courant=0
WQ Output face peclet=0
WQ Output face adv mass=0
WQ Output face disp mass=0
WQ Output cell mass=0
WQ Output cell source sink temp=0
WQ Output nsm pathways=0
WQ Output nsm derived pathways=0
WQ Create Restart=0
WQ Fixed Restart=0
WQ System Summary=0
WQ Write To DSS=0
Sorting and Armoring Iterations= 10
XS Update Threshold= 0.02
Bed Roughness Predictor= 0
Hydraulics Update Threshold= 0.02
Energy Slope Method= 1
Volume Change Method= 1
Sediment Retention Method= 0
Sediment TS Multiplier= 1
Warm Up Method= 0
XS Weighting Method= 0
Number of US Weighted Cross Sections= 1
Number of DS Weighted Cross Sections= 1
Upstream XS Weight=0
Main XS Weight=1
Downstream XS Weight=0
Number of DS XS's Weighted with US Boundary= 1
Upstream Boundary Weight= 1
Weight of XSs Associated with US Boundary= 0
Number of US XS's Weighted with DS Boundary= 1
Downstream Boundary Weight= 0.5
Weight of XSs Associated with DS Boundary= 0.5
Percentile Method= 0
Sediment Output Level= 3
Mass or Volume Output= 0
Output Increment Type= 1
Profile and TS Output Increment= 1
Transport Output Increment 1
XS Output Flag= 0
XS Output Increment= 10
Read HDF5 Sediment Hotstart= 0
Sediment Hotstart Type= 0
Write Gradation File= 0
Read Gradation Hotstart= 0
Write HDF5 File= 1
Write Binary Output= 1
Write DSS Sediment File= 0
DSS Sediment Output Type= 1
SV Curve= 0
Specific Gage Flag= 0
Subcell Erosion Methods= 0
Subcell Deposition Methods= 0
Advection Scheme= 1
Matrix Solver= 0
Implicit Weighting Factor= 1
Maximum Outer Loop Convergence Iterations= 5
Convergence Maximum Absolute= 0.001
Convergence RMSE= 0.0001
Grain Fractions Max Abs Error= 0.001
Max Subgrid Regions= 1
Max Subgrid Length Scale= 3.402823E+38
Initial Layer Thickness= 3.402823E+38
Min Layer Thickness= 3.402823E+38
Max Layer Thickness= 3.402823E+38
Number of Layers= 5

--- REDCK2.f01 (steady flow) ---

Flow Title=Flow
Program Version=6.20
Number of Profiles= 1
Profile Names=P100yr
River Rch & RM=REDCK2,Main,2321
     311
Boundary for River Rch & Prof#=REDCK2,Main            , 1
Up Type= 0
Dn Type= 3
Dn Slope=0.05085
DSS Import GetInterval= 0
DSS Import GetPeak= 0
DSS Import FillOption= 0

--- REDCK2.g01 (geometry) ---

Geom Title=Geometry
Program Version=6.20

River Reach=REDCK2          ,Main
Reach XY= 30
2328400.44400002675507.8020000012328464.68000004675525.163000003
     2328555.999675621.3429999952328605.05599999675698.751000002
2328636.42600003675810.8220000122328694.36200002675883.953000009
2328715.02358557675896.9771046042328780.45162465675900.771433443
2328819.87526385675921.9455208332328874.84300002675889.586999998
2328919.28857607675890.0192459672328989.94699998675998.962000012
2329064.94700001676039.5869999982329088.90499999676066.149000019
2329117.04742214 676163.218862282329146.89353405676196.366098374
2329187.12321489676198.1416835192329294.91494583676257.953834042
2329413.31100188676279.6319851432329444.95899999676341.508000001
2329500.68799999 676400.18900001     2329534.021676506.960000008
2329568.39600001676548.6260000172329613.70899999676563.209999993
      2329689.23      676567.8972329749.12599999676640.553000018
2329772.56299998676652.0120000092329853.81300001676634.303000018
2329937.66700003676643.6780000182330107.63845827676629.036553193

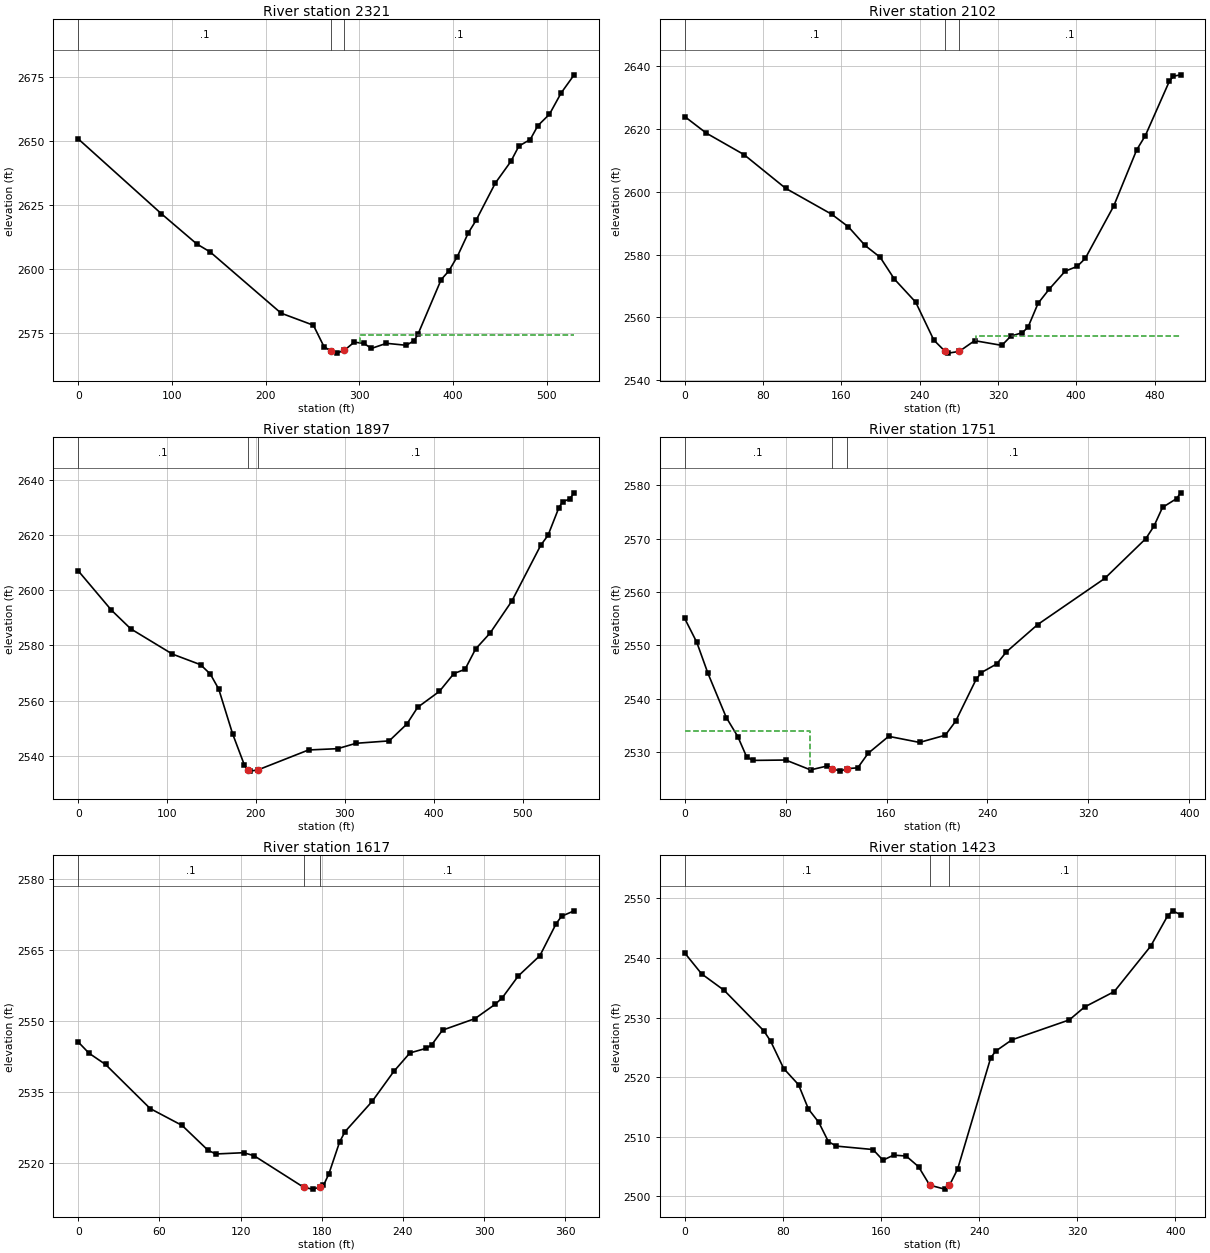
Type RM Length L Ch R = 1 ,2321    ,218.5,218.5,218.5
XS GIS Cut Line= 3
2328209.77540517 675678.295110712328410.24530141675549.297090521
2328482.58878571675267.767627541
#Sta/Elev= 30
       0 2650.76    88.5 2621.69   126.5 2609.85   140.8 2606.73   216.4 2582.91
   250.9 2578.21   262.2 2569.86   269.2 2568.23   275.7 2567.35   283.9 2568.44
   294.4  2571.6   304.6 2571.18   312.8 2569.18   328.8 2571.17     350  2570.4
   358.4 2572.22   362.4 2574.67   387.2 2595.98   395.4 2599.35   404.4 2604.93
   416.1 2614.12   424.4 2619.04     445 2633.57   461.5 2641.96   470.1 2647.96
   482.2 2650.51   490.4 2655.93   502.7 2660.34   515.2 2668.65529.0634  2675.7
#Mann= 3 ,-1,0
       0      .1       0   269.2    .045       0   283.9      .1       0
#XS Ineff= 2 , 0
                          300.51         2574.47
Permanent Ineff=
       F       F
Bank Sta=269.2,283.9
XS Rating Curve= 0 ,0
Exp/Cntr(USF)=0,0
Exp/Cntr=0.3,0.1

Type RM Length L Ch R = 1 ,2102    ,205,205,205
XS GIS Cut Line= 4
2328327.44251818675753.2534197382328542.72975458675673.065461242
2328665.62651706675601.5935851922328694.38958913 675469.98074027
#Sta/Elev= 30
       0 2623.99    22.1  2618.7    60.5 2611.87   103.1 2601.12   150.2 2592.84
   167.3 2588.82   184.3 2582.89   199.7 2579.13   214.2 2572.18     236 2564.82
   254.5 2552.74   265.8 2549.21   269.3 2548.58   280.4 2549.12   296.2 2552.55
     324 2551.05   333.2    2554   344.8 2555.09   350.7 2556.82     361 2564.45
   372.3 2568.94   388.7  2574.7     401 2576.23   409.2 2578.76   438.2 2595.41
   461.8 2613.39   470.6 2617.91   495.2 2635.29   499.3 2636.83506.6237 2637.28
#Mann= 3 ,-1,0
       0      .1       0   265.8    .045       0   280.4      .1       0
#XS Ineff= 2 , 0
                          297.12         2553.94
Permanent Ineff=
       F       F
Bank Sta=265.8,280.4
XS Rating Curve= 0 ,0
Exp/Cntr(USF)=0,0
Exp/Cntr=0.3,0.1

Type RM Length L Ch R = 1 ,1897    ,145.9,145.9,145.9
XS GIS Cut Line= 4
2328477.35913624675918.8589861972328628.14736254675860.461233814
2328706.59210455675800.3202649422328763.24664044675508.331503028
#Sta/Elev= 30
       0 2606.96    37.3 2592.73    59.1 2585.95     106  2576.8   137.6 2572.97
   148.6 2569.59   158.1 2564.13   173.7 2547.94   186.9 2536.69  191.17 2534.78
   193.4 2534.43   202.1 2534.86   259.1 2542.09   291.9 2542.56   312.6 2544.51
   349.9 2545.38   369.7 2551.46   381.9 2557.53   406.4 2563.31   422.7 2569.77
   435.2 2571.28   447.1 2578.65   463.4 2584.41   487.9 2596.02   520.4 2616.21
   528.6 2619.82   540.8 2629.82   544.9 2631.89     553 2633.01557.9818 2635.19
#Mann= 3 ,-1,0
       0      .1       0  191.17    .045       0   202.1      .1       0
Bank Sta=191.17,202.1
XS Rating Curve= 0 ,0
Exp/Cntr(USF)=0,0
Exp/Cntr=0.3,0.1

Type RM Length L Ch R = 1 ,1751    ,134,134,134
XS GIS Cut Line= 4
2328703.40812496 675980.096313652328766.86766988675951.377395511
 2328801.1450883675782.7695535352328829.86400644675634.079670914
#Sta/Elev= 30
       0 2555.06     9.6 2550.58    18.4 2544.79      33 2536.48    42.1 2532.92
    49.1 2529.12    54.2 2528.45    80.1 2528.52    99.8 2526.67   112.7 2527.39
   116.4 2526.93   123.5 2526.44     129 2526.91   137.2 2527.06   145.4 2529.77
   161.7 2532.96   186.2 2531.82   206.6 2533.17   214.8 2535.79   231.1 2543.66
   235.2 2544.91   247.4 2546.53     255 2548.78   279.8  2553.9     333 2562.55
   365.6 2570.02     372 2572.34   378.8 2575.86     390 2577.51393.1503 2578.59
#Mann= 3 ,-1,0
       0      .1       0   116.4    .045       0     129      .1       0
#XS Ineff= 2 , 0
           99.09 2533.92
Permanent Ineff=
       F       F
Bank Sta=116.4,129
XS Rating Curve= 0 ,0
Exp/Cntr(USF)=0,0
Exp/Cntr=0.3,0.1

Type RM Length L Ch R = 1 ,1617    ,193.9,193.9,193.9
XS GIS Cut Line= 4
 2328790.9038615676011.0385098312328851.63562387675941.557256269
2328894.35372791675916.8528105582328898.47113553675691.939419399
#Sta/Elev= 30
       0 2545.53       8 2543.16    20.2 2540.79    53.2 2531.49    76.8 2527.93
    95.9 2522.71   101.7 2521.91   122.2 2522.18   129.9 2521.56   166.92514.847
   173.3  2514.5     1792514.938   181.3 2515.28   185.3 2517.73   193.3 2524.51
   197.3 2526.64   217.3 2533.01   233.3 2539.33   245.2 2543.22   257.3  2544.2
   261.3 2544.94   269.3 2548.03   293.3 2550.46   308.1 2553.46   313.3 2554.79
   325.3 2559.45   341.3 2563.74   353.3 2570.49   357.3 2572.05   366.6 2573.19
#Mann= 3 ,-1,0
       0      .1       0   166.9    .045       0     179      .1       0
Bank Sta=166.9,179
XS Rating Curve= 0 ,0
Exp/Cntr(USF)=0,0
Exp/Cntr=0.3,0.1

Type RM Length L Ch R = 1 ,1423    ,85.1,85.1,85.1
XS GIS Cut Line= 4
 2328836.3757415676077.0751860662329003.54763757676052.061934784
2329040.65062697675984.5261563222329046.90393979675826.525785724
#Sta/Elev= 30
       0 2540.85    13.8 2537.33    32.2 2534.56    64.5 2527.76    70.1 2526.01
    80.7 2521.43    92.8 2518.71   100.9 2514.61   109.3 2512.39   117.1 2509.16
   123.5  2508.4   153.5 2507.82   161.6 2506.03   170.3 2506.88   180.5 2506.73
   190.6 2504.94   199.7 2501.84   211.9 2501.17   215.8  2501.8   222.5 2504.56
   249.4 2523.21   253.4 2524.34   266.7 2526.25   313.5  2529.6   325.9 2531.76
   350.1 2534.35   379.8 2541.98   393.6 2547.07   397.6 2547.92404.2135 2547.28
#Mann= 3 ,-1,0
       0      .1       0   199.7    .045       0   215.8      .1       0
Bank Sta=199.7,215.8
XS Rating Curve= 0 ,0
Exp/Cntr(USF)=0,0
Exp/Cntr=0.3,0.1

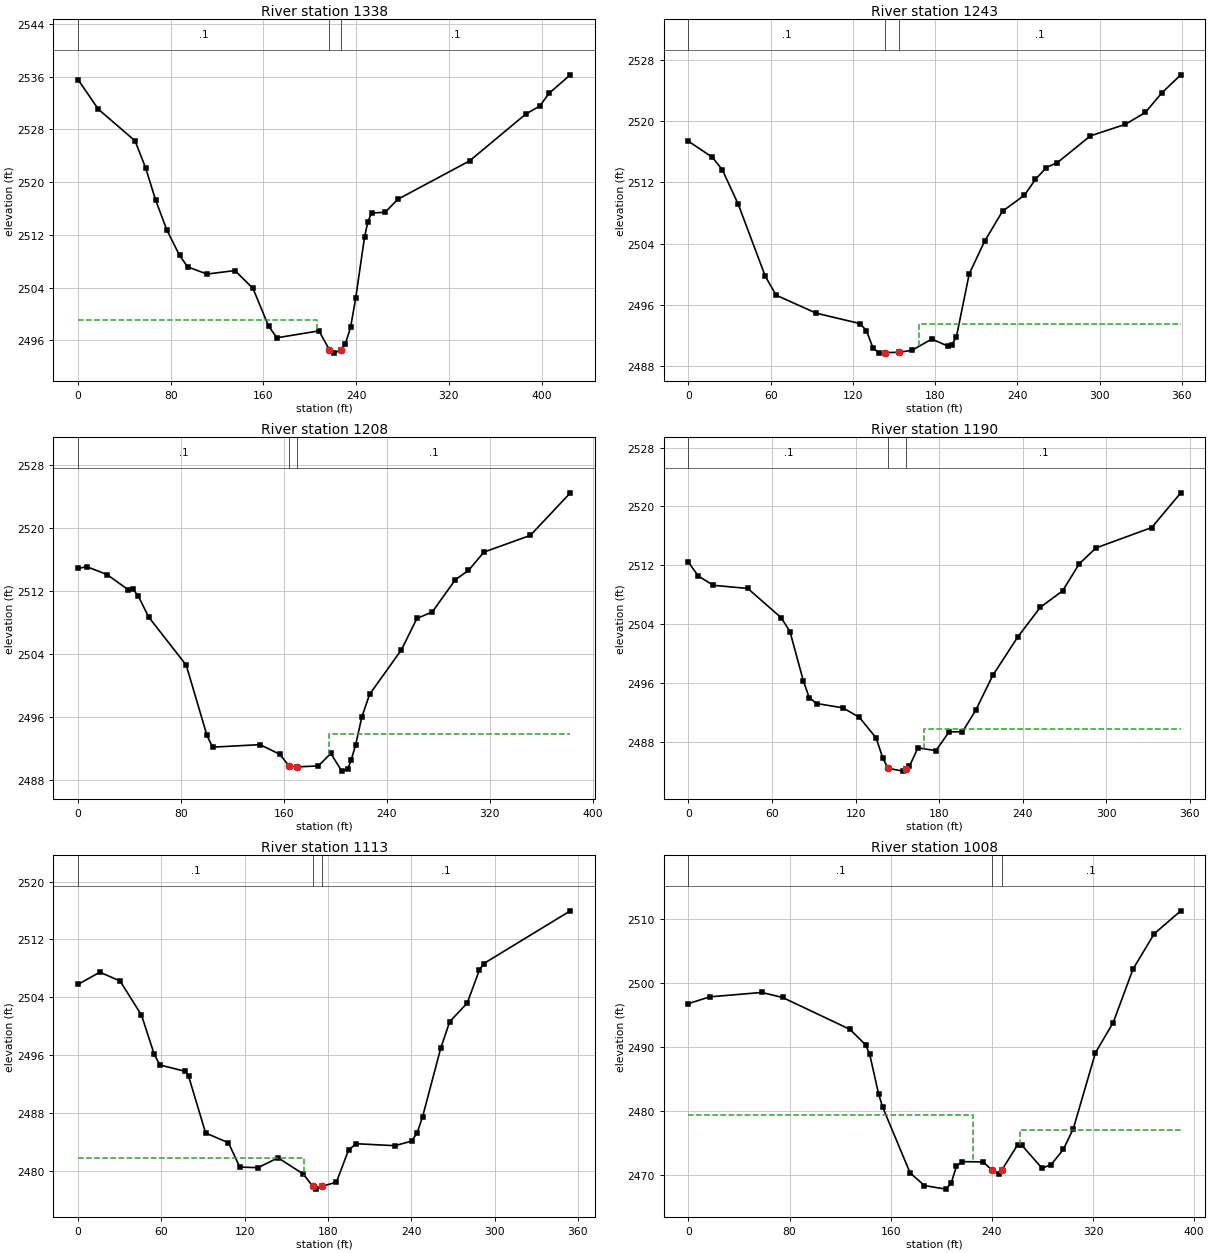
Type RM Length L Ch R = 1 ,1338    ,95.3,95.3,95.3
XS GIS Cut Line= 3
2328892.72888743 676172.303294632329150.33754637676034.782882718
2329132.90538148675903.073192435
#Sta/Elev= 30
       0 2535.56    17.5 2531.07    49.2 2526.27    58.3 2522.19    66.9 2517.32
    76.5 2512.81    87.6  2508.9    94.6 2507.16   111.3 2506.07   135.4  2506.6
     151 2503.89   164.5 2498.14   171.7 2496.41   207.9 2497.45     217 2494.58
   220.7 2494.08   226.6 2494.53   230.6 2495.44   235.2 2497.98   239.7 2502.51
   247.3 2511.73   250.2 2514.02   253.3 2515.33     265 2515.43     276 2517.41
   337.9 2523.23   386.4 2530.33   398.5 2531.55   406.6  2533.5424.8755 2536.28
#Mann= 3 ,-1,0
       0      .1       0     217    .045       0   226.6      .1       0
#XS Ineff= 2 , 0
          206.33 2499.11
Permanent Ineff=
       F       F
Bank Sta=217,226.6
XS Rating Curve= 0 ,0
Exp/Cntr(USF)=0,0
Exp/Cntr=0.3,0.1

Type RM Length L Ch R = 1 ,1243    ,35.6,35.6,35.6
XS GIS Cut Line= 4
 2328988.9195051  676233.77435782329046.24398559676199.757136663
2329167.48531011676125.5447402952329159.42650134675975.304094551
#Sta/Elev= 30
       0 2517.38    17.4 2515.29    24.7 2513.66    36.3 2509.16      56 2499.77
    63.9 2497.28    93.2 2494.92   125.2 2493.56   129.9 2492.64   134.6 2490.39
   139.3  2489.7143.1361 2489.76153.30982489.808     163 2490.06   177.6 2491.54
   189.2 2490.62   192.1 2490.77   195.5 2491.79   204.9 2500.06   216.1 2504.31
   229.2 2508.24   245.2 2510.33   253.2  2512.4   261.2 2513.95   269.3  2514.6
   293.3 2518.08   318.8 2519.59   333.4 2521.14   345.4 2523.69   359.3 2526.06
#Mann= 3 ,-1,0
       0      .1       0143.1361    .045       0153.3098      .1       0
#XS Ineff= 2 , 0
                          168.11         2493.54
Permanent Ineff=
       F       F
Bank Sta=143.1361,153.3098
XS Rating Curve= 0 ,0
Exp/Cntr(USF)=0,0
Exp/Cntr=0.3,0.1

Type RM Length L Ch R = 1 ,1208    ,17.2,17.2,17.2
XS GIS Cut Line= 4
2328997.42821726676244.6758444062329081.43959898676247.511963064
2329178.53563191676138.352434132 2329167.9352135675986.205581157
#Sta/Elev= 30
       0 2514.85     6.8 2515.07    22.5 2514.08    38.8 2512.17    42.8 2512.19
    46.8 2511.36    54.8 2508.71    84.1 2502.58   100.2 2493.68   104.6 2492.18
   141.5  2492.5   156.8 2491.28   164.1 2489.78170.4395 2489.68   186.8  2489.8
   196.5 2491.39     205 2489.14   209.5 2489.38   212.3 2490.53   215.7 2492.41
   220.6 2495.99   226.6 2498.87   251.4 2504.53   263.4  2508.5   275.4 2509.34
   293.4 2513.44   303.5 2514.59   315.5 2516.92   351.6 2519.04   382.7 2524.44
#Mann= 3 ,-1,0
       0      .1       0   164.1    .045       0170.4395      .1       0
#XS Ineff= 2 , 0
                          195.38         2493.84
Permanent Ineff=
       F       F
Bank Sta=164.1,170.4395
XS Rating Curve= 0 ,0
Exp/Cntr(USF)=0,0
Exp/Cntr=0.3,0.1

Type RM Length L Ch R = 1 ,1190    ,77,77,77
XS GIS Cut Line= 4
2329033.58370494676265.3479935962329103.52816686676267.664035381
2329185.51604606676140.7449455422329187.83208784676008.267355417
#Sta/Elev= 30
       0  2512.4       7 2510.54    17.8 2509.27    42.6 2508.84    66.6 2504.86
    72.9 2502.97    82.5 2496.28    86.7 2494.01      92  2493.2     111 2492.61
   122.8 2491.31   134.8 2488.51   139.6 2485.76   143.4  2484.4   153.9 2484.01
   156.1 2484.36   158.7 2484.68   164.8 2487.17   177.7  2486.8   187.2 2489.35
   196.8 2489.36   206.3 2492.28   218.6 2497.04   236.6 2502.27   252.7 2506.28
   268.7 2508.51   280.7  2512.2   292.7 2514.35   332.7 2517.12   353.6 2521.84
#Mann= 3 ,-1,0
       0      .1       0   143.4    .045       0   156.1      .1       0
#XS Ineff= 2 , 0
                          168.91         2489.67
Permanent Ineff=
       F       F
Bank Sta=143.4,156.1
XS Rating Curve= 0 ,0
Exp/Cntr(USF)=0,0
Exp/Cntr=0.3,0.1

Type RM Length L Ch R = 1 ,1113    ,105.4,105.4,105.4
XS GIS Cut Line= 4
 2329070.6403735676282.4867028072329195.24342156676253.767784669
2329247.58596591676174.5591556082329239.24821548676043.007982198
#Sta/Elev= 30
       0 2505.78    15.7 2507.47    30.3 2506.25    45.7 2501.53    54.9  2496.1
      59 2494.63    77.1 2493.76    79.6  2493.1    91.9 2485.22   108.3 2483.88
   116.5 2480.51   129.6 2480.43   144.1 2481.79   162.1 2479.57   169.1 2477.85
   171.7 2477.46   175.52477.846   186.1 2478.42   194.9  2482.9   200.5 2483.74
   228.2 2483.47   240.2  2484.1   244.2 2485.21   248.2  2487.5   261.2 2496.93
   267.7 2500.63   280.3 2503.19   289.1 2507.78   292.3 2508.67   354.6 2515.96
#Mann= 3 ,-1,0
       0      .1       0   169.1    .045       0   175.5      .1       0
#XS Ineff= 2 , 0
          163.03 2481.75
Permanent Ineff=
       F       F
Bank Sta=169.1,175.5
XS Rating Curve= 0 ,0
Exp/Cntr(USF)=0,0
Exp/Cntr=0.3,0.1

Type RM Length L Ch R = 1 ,1008    ,49.6,49.6,49.6
XS GIS Cut Line= 4
2329131.82642732676315.0814411652329271.54435731676348.298867167
2329288.48385604676330.687654166 2329360.2535938676121.248405903
#Sta/Elev= 30
       0  2496.8    16.8 2497.85    57.9 2498.54    74.4 2497.76   127.8 2492.77
   140.1 2490.36   143.3 2488.91   150.3 2482.75   153.5 2480.68   175.3 2470.37
   186.6  2468.4   203.5 2467.84   207.7 2468.72   211.9 2471.38   216.2 2472.13
   233.1 2472.09  240.11 2470.78   245.8 2470.13   247.7 2470.77   260.3 2474.75
   263.5 2474.73   279.6 2471.11   286.8 2471.65   296.5 2474.04   304.4 2477.28
   321.9 2489.13   335.9 2493.82   351.6 2502.18   368.4 2507.71   389.4 2511.28
#Mann= 3 ,-1,0
       0      .1       0  240.11    .045       0   247.7      .1       0
#XS Ineff= 2 , 0
          225.14 2479.36  261.84         2477.04
Permanent Ineff=
       F       F
Bank Sta=240.11,247.7
XS Rating Curve= 0 ,0
Exp/Cntr(USF)=0,0
Exp/Cntr=0.3,0.1

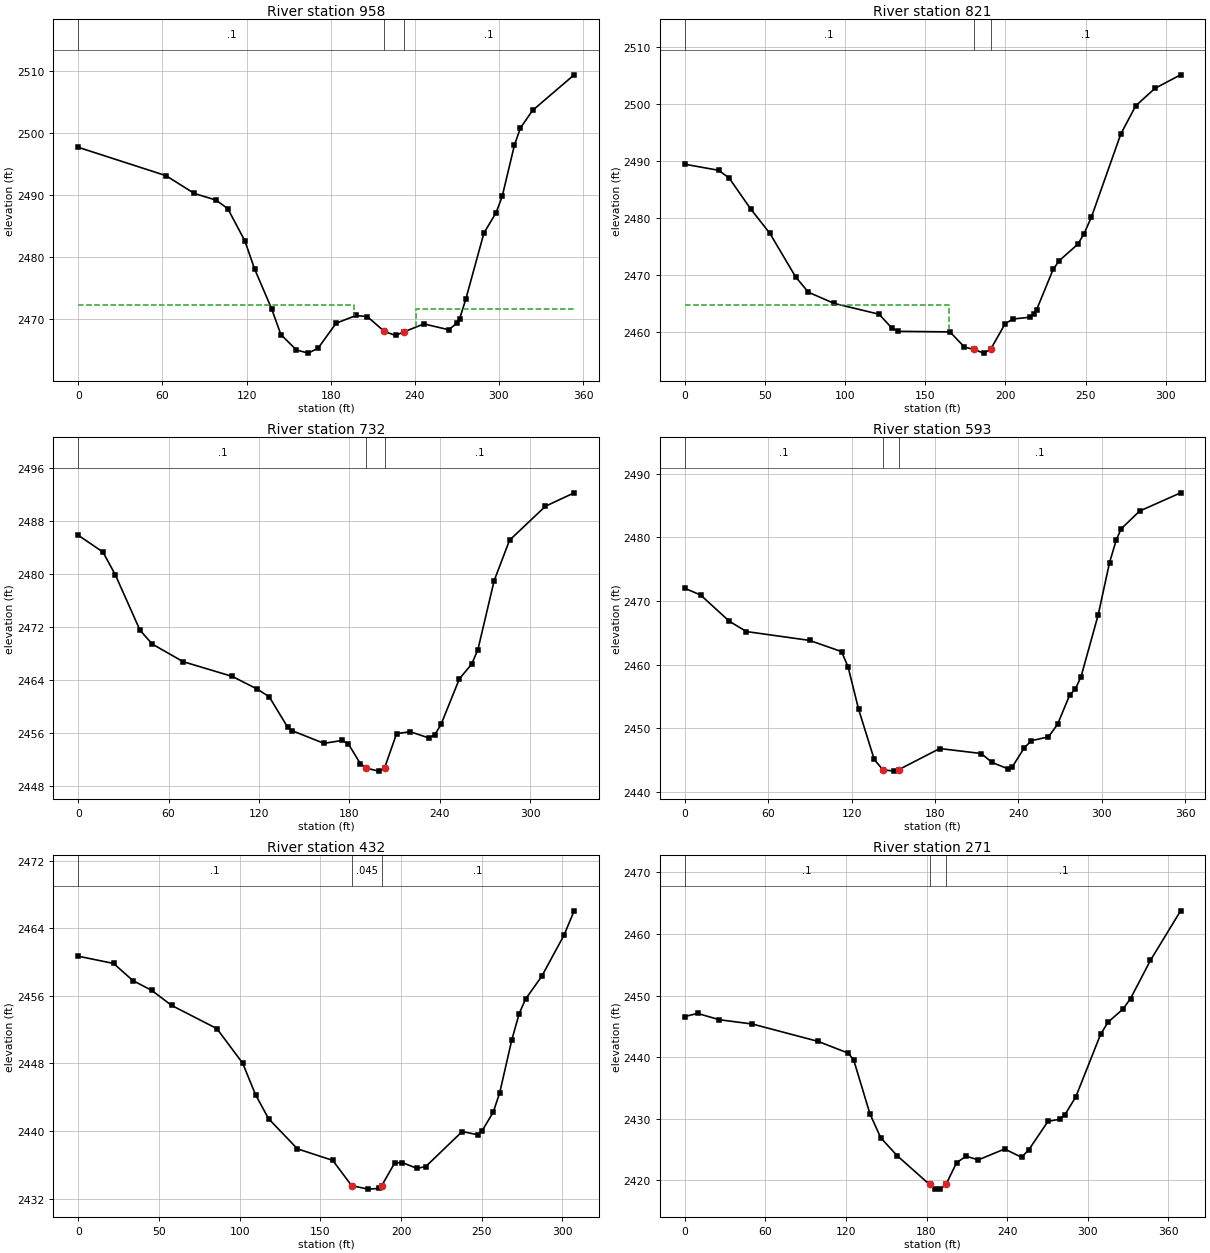
Type RM Length L Ch R = 1 ,958     ,137.1,137.1,137.1
XS GIS Cut Line= 5
2329190.51438848676351.8292717872329295.57004386676369.755435206
 2329356.8525095676299.7183316162329363.52270985676245.939841359
2329401.87636181676153.807699136
#Sta/Elev= 30
       0 2497.72    62.6 2493.15    82.8 2490.28    98.2 2489.22   106.6 2487.85
   118.8 2482.66   125.7 2478.16   137.9 2471.71   144.5 2467.56   155.6 2465.07
   164.1 2464.57   171.1 2465.39   183.9 2469.39   198.1 2470.63   206.2 2470.44
   218.3 2468.06   226.3 2467.41   232.12467.982   246.5 2469.27   264.1 2468.34
   270.2 2469.41     272 2470.14   276.3 2473.23   289.3 2483.93     298 2487.21
   302.3 2489.82     311 2498.04   315.3 2500.84     324 2503.67   353.6 2509.39
#Mann= 3 ,-1,0
       0      .1       0   218.3    .045       0   232.1      .1       0
#XS Ineff= 2 , 0
          196.72 2472.27  240.59         2471.62
Permanent Ineff=
       F       F
Bank Sta=218.3,232.1
XS Rating Curve= 0 ,0
Exp/Cntr(USF)=0,0
Exp/Cntr=0.3,0.1

Type RM Length L Ch R = 1 ,821     ,89,89,89
XS GIS Cut Line= 5
2329275.14255532676377.259410591 2329368.5253601676372.256760334
2329436.92095099676372.0608234132329475.54093541676317.745206317
2329479.00055327 676237.18520341
#Sta/Elev= 30
       0 2489.42    21.1 2488.36    27.7 2487.01    41.1  2481.6    53.1 2477.31
    69.1  2469.7    77.1 2466.99    93.2 2465.02   121.2 2463.13   129.2 2460.69
   133.2 2460.13   165.4 2460.03   174.4 2457.37   180.2 2456.97   186.4 2456.31
  190.73 2456.97   199.8 2461.47   204.7 2462.29   215.1  2462.6   217.9 2463.25
   219.4 2463.91   229.7 2470.97   233.5 2472.51   245.1  2475.4   248.9 2477.19
   253.6 2480.16   271.9 2494.71   281.2 2499.66   293.2 2502.72   309.2 2505.09
#Mann= 3 ,0,0
       0      .1       0   180.2    .045       0  190.73      .1       0
#XS Ineff= 2 , 0
           164.5 2464.77
Permanent Ineff=
       F       F
Bank Sta=180.2,190.73
XS Rating Curve= 0 ,0
Exp/Cntr(USF)=0,0
Exp/Cntr=0.3,0.1

Type RM Length L Ch R = 1 ,732     ,139.6,139.6,139.6
XS GIS Cut Line= 4
2329312.07763722676396.5510494492329446.92414873676424.791156571
2329525.99644867676416.3191244352329547.96866402676306.458047702
#Sta/Elev= 30
       0 2485.85    16.4 2483.32    24.6  2479.9      41 2471.53    49.1 2469.44
    69.6 2466.78   102.3 2464.55   118.6 2462.67   126.8 2461.49     139 2456.91
   142.2 2456.34   163.2 2454.45   175.2 2454.89   179.3  2454.4   187.3  2451.4
   191.3 2450.72   199.4 2450.26   203.4 2450.73   211.4 2455.92   220.5  2456.2
   232.7 2455.27   236.8 2455.76   240.9  2457.3   253.1 2464.19   261.3 2466.42
   265.4 2468.61   276.2 2479.01   286.4  2485.1   310.2 2490.22   329.3 2492.25
#Mann= 3 ,-1,0
       0      .1       0   191.3    .045       0   203.4      .1       0
Bank Sta=191.3,203.4
XS Rating Curve= 0 ,0
Exp/Cntr(USF)=0,0
Exp/Cntr=0.3,0.1

Type RM Length L Ch R = 1 ,593     ,160.5,160.5,160.5
XS GIS Cut Line= 4
2329437.04011124676553.9896466562329539.41049956676579.405743067
2329626.95483163676438.2052074552329645.51283568676355.279184834
#Sta/Elev= 30
       0    2472    11.5 2470.93    32.1 2466.81    44.4 2465.19    89.8  2463.8
   112.8 2462.04   117.5 2459.63   125.1 2452.94   136.3 2445.08   142.5 2443.46
   150.5 2443.25   154.1  2443.5   183.4  2446.8   213.2 2446.02     221 2444.62
   232.6  2443.6   235.5 2443.89   244.2 2446.92   249.3 2448.03   261.6 2448.64
   268.1  2450.6   276.8  2455.2   280.9 2456.16     285  2458.1   297.3 2467.79
   305.5 2476.04   310.3 2479.57   313.8 2481.33   327.1 2484.13   356.6    2487
#Mann= 3 ,-1,0
       0      .1       0   142.5    .045       0   154.1      .1       0
Bank Sta=142.5,154.1
XS Rating Curve= 0 ,0
Exp/Cntr(USF)=0,0
Exp/Cntr=0.3,0.1

Type RM Length L Ch R = 1 ,432     ,160.7,160.7,160.7
XS GIS Cut Line= 4
2329554.23655579676633.0619465992329677.08102178676634.473951955
 2329746.9752869676527.8675475682329739.91526012676471.387333324
#Sta/Elev= 30
       0 2460.68    21.9 2459.82    33.9 2457.79    45.5 2456.64    57.9 2454.85
    85.9 2452.11   101.9 2448.01   109.9 2444.27   117.9 2441.45   135.8 2437.88
   157.7 2436.51   169.4 2433.52   179.6 2433.11   186.6 2433.19  188.01 2433.51
   196.1 2436.22   200.9 2436.24   209.8 2435.57   215.3 2435.78   237.9 2439.93
   247.4 2439.55   250.3 2440.04   257.1 2442.21   261.1  2444.5   268.6 2450.76
   273.2 2453.89   277.2 2455.62   287.1 2458.28   300.9 2463.14307.2484 2466.05
#Mann= 3 ,-1,0
       0      .1       0   169.4    .045       0  188.01      .1       0
Bank Sta=169.4,188.01
XS Rating Curve= 0 ,0
Exp/Cntr(USF)=0,0
Exp/Cntr=0.3,0.1

Type RM Length L Ch R = 1 ,271     ,76.1,76.1,76.1
XS GIS Cut Line= 4
2329730.73722531676726.9603027812329846.52166451676705.074219761
2329823.92957881  676523.63153152329776.62739938676474.211344036
#Sta/Elev= 30
       0 2446.58     9.6 2447.09    25.9 2446.06    50.3 2445.37    99.2 2442.55
   121.8 2440.63   125.8 2439.51   137.9 2430.76   145.9 2426.89     158    2424
   182.2  2419.3   186.3 2418.54   190.3 2418.56  194.56 2419.34   202.4 2422.85
   209.5 2423.89   218.5 2423.29   238.1 2425.06   250.7 2423.72   256.1 2424.93
   270.4 2429.56     279 2429.89     283 2430.64   291.1 2433.54   309.6 2443.73
   315.1 2445.67   326.2  2447.8   331.8  2449.5   346.6  2455.7 369.088 2463.76
#Mann= 3 ,-1,0
       0      .1       0   182.2    .045       0  194.56      .1       0
Bank Sta=182.2,194.56
XS Rating Curve= 0 ,0
Exp/Cntr(USF)=0,0
Exp/Cntr=0.3,0.1

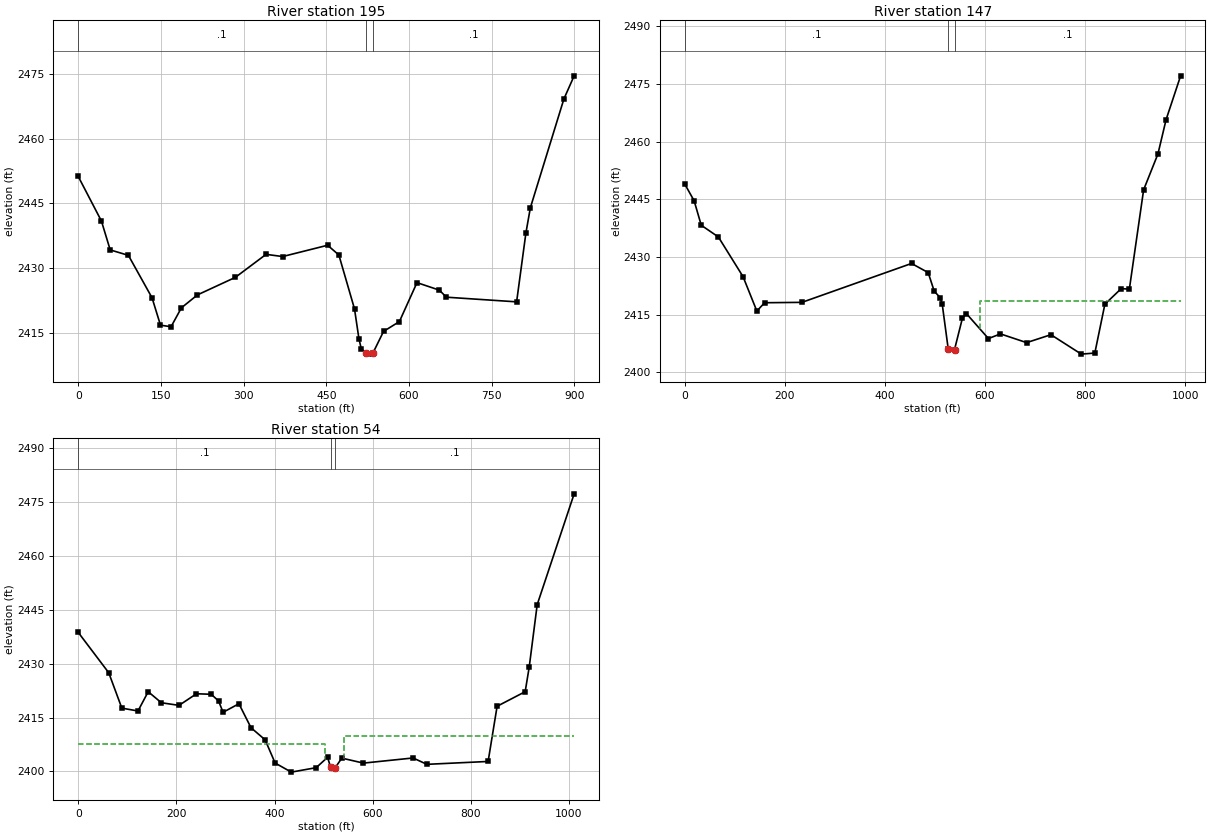
Type RM Length L Ch R = 1 ,195     ,48.4,48.4,48.4
XS GIS Cut Line= 6
2329871.69483007677122.1611873052329980.64586064676984.447084672
2329919.63328352676680.2558073362329892.61342794676502.447725455
2329864.72196412    676376.064532329761.87219126 676358.63236511
#Sta/Elev= 30
       0 2451.26    42.1 2440.91      58 2434.21      91 2432.95   133.9  2423.1
   149.2 2416.75   168.4 2416.38   187.1 2420.77   216.2 2423.77     285 2427.84
   340.7 2433.18   370.7 2432.67   452.3 2435.29   472.7 2433.04   501.1 2420.52
   509.2 2413.53   513.3  2411.3   521.4 2410.34   533.5 2410.03  534.58  2410.3
   553.8 2415.31   582.5 2417.58   614.4 2426.62   654.9 2424.88   667.7 2423.24
   795.1 2422.16   811.9  2438.1     820 2443.98   880.9 2469.25899.4454  2474.6
#Mann= 3 ,0,0
       0      .1       0   521.4    .045       0  534.58      .1       0
Bank Sta=521.4,534.58
XS Rating Curve= 0 ,0
Exp/Cntr(USF)=0,0
Exp/Cntr=0.3,0.1

Type RM Length L Ch R = 1 ,147     ,92.8,92.8,92.8
XS GIS Cut Line= 6
2329913.09622169677132.6204862392330022.04725225676994.906383606
2329965.52549372676689.0931004872329951.44698445676505.934158433
2329927.91356184 676358.632365112329759.69317065676325.511251819
#Sta/Elev= 30
       0 2448.98    18.9 2444.59    33.1 2438.24    67.3 2435.19   116.6 2424.88
   144.2 2415.93   159.7 2418.09   234.3 2418.19   453.3  2428.3   486.5 2425.93
   498.6  2421.1   510.6  2419.4   514.6  2417.7   526.7 2405.95  539.17 2405.92
   554.8 2414.01   562.8 2415.28   606.9 2408.78     631 2409.99   683.2 2407.72
   731.8 2409.78   792.5 2404.73   819.5 2405.01   839.6 2417.71   872.2 2421.76
   888.5 2421.63     917 2447.45   945.6 2456.77   961.9  2465.7990.9174 2477.08
#Mann= 3 ,-1,0
       0      .1       0   526.7    .045       0  539.17      .1       0
#XS Ineff= 2 , 0
                           589.6         2418.59
Permanent Ineff=
       F       F
Bank Sta=526.7,539.17
XS Rating Curve= 0 ,0
Exp/Cntr(USF)=0,0
Exp/Cntr=0.3,0.1

Type RM Length L Ch R = 1 ,54      ,,,
XS GIS Cut Line= 6
 2329972.5562547677116.899805581 2330104.0746455676852.667402237
2330050.32104662676618.8033127032329965.60072526676488.585040973
2329930.06525713676348.1689527812329758.50660636  676312.1628162
#Sta/Elev= 30
       0 2438.72    62.2 2427.48    88.9 2417.63   121.8 2416.84   142.6  2422.2
   169.5 2419.13   205.4  2418.4     241 2421.63     271 2421.49   285.9 2419.65
   295.2 2416.48   327.5 2418.85   352.1 2412.18   380.8 2408.82   401.3 2402.35
   434.2 2399.82   484.9 2401.06   508.1 2403.94  514.51 2401.11  523.99  2401.1
   537.1 2403.72   581.2 2402.33   682.4 2403.76   710.5 2401.99   835.3 2402.79
   853.6 2418.15   910.8 2422.21     919 2429.04   935.3 2446.441010.608 2477.28
#Mann= 3 ,-1,0
       0      .1       0  514.51    .045       0  523.99      .1       0
#XS Ineff= 2 , 0
          502.66 2407.64  542.08         2409.87
Permanent Ineff=
       F       F
Bank Sta=514.51,523.99
XS Rating Curve= 0 ,0
Exp/Cntr(USF)=0,0
Exp/Cntr=0.3,0.1
LCMann Table=0

Chan Stop Cuts=-1
Use User Specified Reach Order=0
Composite Channel Slope=5